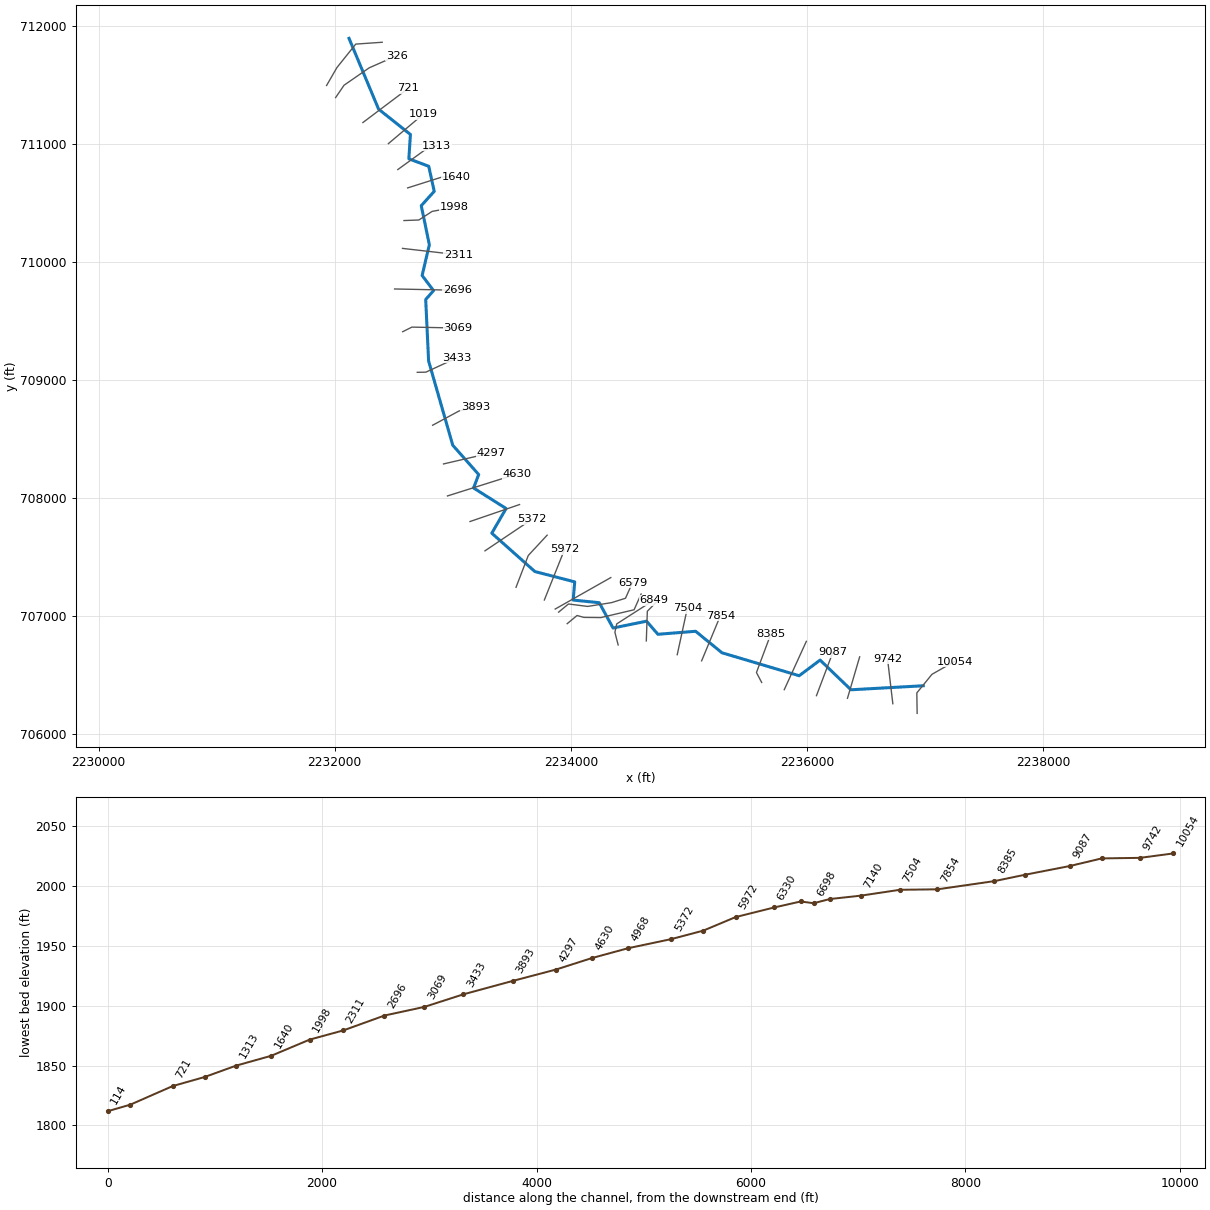
--- MIDFKRIVT1.prj (project) ---

Proj Title=MIDFKRIVT1
Current Plan=p01
Default Exp/Contr=0,0
English Units
Geom File=g01
Flow File=f01
Plan File=p01
BEGIN DESCRIPTION:
----------MODEL BY WOOD PLC 2022----------
AFH study
Randolph County, WV
HEC-RAS Version: RAS 6.2
Vertical Datum: NAVD88
Projection: NAD 1983 StatePlane West Virginia S FIPS 4702 (US Feet)
Terrain: 1-meter LIDAR (FEMA Region III 3DEP collected 2016-2018)
Land Use: 2019 NLCD
Hydrologic Method:
WV SIR2010-5033 regression equations
Additional Model Notes:
DS extent goes beyond county boundary into Barbour, main stem is MIDFKRIV2.
END DESCRIPTION:
DSS File=dss
DSS Export Rating Curves= 0
DSS Export Rating Curve Sorted= 0
DSS Export Volume Flow Curves= 0
DXF OffsetX= 0
DXF OffsetY= 0
DXF ScaleX= 0
DXF ScaleY= 0

--- MIDFKRIVT1.p01 (plan) ---

Plan Title=Floodplain
Program Version=6.20
Short Identifier=Floodplain
Geom File=g01
Flow File=f01
Subcritical Flow
K Sum by GR= 0
Std Step Tol= 0.01
Critical Tol= 0.01
Num of Std Step Trials= 20
Max Error Tol= 0.3
Flow Tol Ratio= 0.001
Split Flow NTrial= 30
Split Flow Tol= 0.02
Split Flow Ratio= 0.02
Log Output Level= 0
Friction Slope Method= 1
Unsteady Friction Slope Method= 2
Unsteady Bridges Friction Slope Method= 1
Parabolic Critical Depth
Global Vel Dist= 0 , 0 , 0
Global Log Level= 0
CheckData=True
Encroach Param=-1 ,0,0, 0
Computation Interval=0.1SEC
Output Interval=1SEC
Instantaneous Interval=Max Profile
Mapping Interval=1HOUR
Computation Time Step Use Courant=        0
Computation Time Step Use Time Series=    0
Computation Time Step Count To Double=0
Computation Time Step Max Doubling=0
Computation Time Step Max Halving=0
Computation Time Step Residence Courant=0
Run HTab= 0
Run UNet= 0
Run Sediment= 0
Run PostProcess= 0
Run WQNet= 0
Run RASMapper=-1
UNET Theta= 0
UNET Theta Warmup= 0
UNET ZTol= 0
UNET ZSATol= 0
UNET MxIter= 0
UNET Max Iter WO Improvement= 0
UNET MaxInSteps= 0
UNET DtIC= 0
UNET DtMin= 0
UNET MaxCRTS= 0
UNET WFStab= 0
UNET SFStab= 0
UNET WFX= 1
UNET SFX= 1
UNET Gravity=32.174
UNET 1D Methodology=Finite Difference
UNET DSS MLevel= 1
UNET Pardiso=0
UNET DZMax Abort= 0
UNET Use Existing IB Tables= 0
UNET Froude Reduction=False
UNET Froude Limit= 0
UNET Froude Power= 0
UNET D1 Cores= 0
UNET WindReference=Eulerian
UNET WindDragFormulation=Hsu (1988)
UNET D2 Coriolis=0
UNET D2 Cores= 0
UNET D2 Theta= 1
UNET D2 Theta Warmup= 1
UNET D2 Z Tol= 0.01
UNET D2 Volume Tol= 0.01
UNET D2 Max Iterations= 20
UNET D2 Equation= 0
UNET D2 RampUpFraction=0.1
UNET D2 TimeSlices= 1
UNET D2 Turbulence Formulation=Non-Conservative (original)
UNET D2 Eddy Viscosity=0.3
UNET D2 Transverse Eddy Viscosity=0.1
UNET D2 Smagorinsky Mixing=0
UNET D2 BCVolumeCheck=0
UNET D2 Cores=0
UNET D2 SolverType=PARDISO (Direct)
UNET D2 Minimum Iterations= 2147483647
UNET D2 Maximum Iterations= 2147483647
UNET D2 Restart Number= 10
UNET D2 Relaxation Coeff=1.3
UNET D2 SOR Precondition Iterations= 10
UNET D2 ILUT Maximum Fill= 8
UNET D2 ILUT Tolerance=1E-08
UNET D1D2 MaxIter= 0
UNET D1D2 ZTol=0.01
UNET D1D2 QTol=0.1
UNET D1D2 MinQTol=1
DSS File=dss
Write IC File= 0
Write IC File at Fixed DateTime=0
Write IC File at Sim End=0
Echo Input=False
Echo Parameters=False
Echo Output=False
Write Detailed= 0
HDF Write Warmup=0
HDF Write Time Slices=0
HDF Flush=0
HDF Compression= 1
HDF Chunk Size= 1
HDF Spatial Parts= 1
HDF Use Max Rows=0
HDF Fixed Rows= 1
Calibration Method= 0
Calibration Iterations= 20
Calibration Max Change=0.05
Calibration Tolerance=0.2
Calibration Maximum=1.5
Calibration Minimum=0.5
Calibration Optimization Method= 1
WQ AD Non Conservative
WQ ULTIMATE=-1
WQ Max Comp Step=1HOUR
WQ Output Interval=15MIN
WQ Output Selected Increments= 0
WQ Output face flow=0
WQ Output face velocity=0
WQ Output face area=0
WQ Output face dispersion=0
WQ Output cell volume=0
WQ Output cell surface area=0
WQ Output cell continuity=0
WQ Output cumulative cell continuity=0
WQ Output face conc=0
WQ Output face dconc_dx=0
WQ Output face courant=0
WQ Output face peclet=0
WQ Output face adv mass=0
WQ Output face disp mass=0
WQ Output cell mass=0
WQ Output cell source sink temp=0
WQ Output nsm pathways=0
WQ Output nsm derived pathways=0
WQ Create Restart=0
WQ Fixed Restart=0
WQ System Summary=0
WQ Write To DSS=0
Sorting and Armoring Iterations= 10
XS Update Threshold= 0.02
Bed Roughness Predictor= 0
Hydraulics Update Threshold= 0.02
Energy Slope Method= 1
Volume Change Method= 1
Sediment Retention Method= 0
Sediment TS Multiplier= 1
Warm Up Method= 0
XS Weighting Method= 0
Number of US Weighted Cross Sections= 1
Number of DS Weighted Cross Sections= 1
Upstream XS Weight=0
Main XS Weight=1
Downstream XS Weight=0
Number of DS XS's Weighted with US Boundary= 1
Upstream Boundary Weight= 1
Weight of XSs Associated with US Boundary= 0
Number of US XS's Weighted with DS Boundary= 1
Downstream Boundary Weight= 0.5
Weight of XSs Associated with DS Boundary= 0.5
Percentile Method= 0
Sediment Output Level= 3
Mass or Volume Output= 0
Output Increment Type= 1
Profile and TS Output Increment= 1
Transport Output Increment 1
XS Output Flag= 0
XS Output Increment= 10
Read HDF5 Sediment Hotstart= 0
Sediment Hotstart Type= 0
Write Gradation File= 0
Read Gradation Hotstart= 0
Write HDF5 File= 1
Write Binary Output= 1
Write DSS Sediment File= 0
DSS Sediment Output Type= 1
SV Curve= 0
Specific Gage Flag= 0
Subcell Erosion Methods= 0
Subcell Deposition Methods= 0
Advection Scheme= 1
Matrix Solver= 0
Implicit Weighting Factor= 1
Maximum Outer Loop Convergence Iterations= 5
Convergence Maximum Absolute= 0.001
Convergence RMSE= 0.0001
Grain Fractions Max Abs Error= 0.001
Max Subgrid Regions= 1
Max Subgrid Length Scale= 3.402823E+38
Initial Layer Thickness= 3.402823E+38
Min Layer Thickness= 3.402823E+38
Max Layer Thickness= 3.402823E+38
Number of Layers= 5

--- MIDFKRIVT1.f01 (steady flow) ---

Flow Title=Flow
Program Version=6.20
Number of Profiles= 1
Profile Names=P100yr
River Rch & RM=MIDFKRIVT1,Main,10054
     367
River Rch & RM=MIDFKRIVT1,Main,7140
     411
River Rch & RM=MIDFKRIVT1,Main,4297
     458
River Rch & RM=MIDFKRIVT1,Main,2311
     512
Boundary for River Rch & Prof#=MIDFKRIVT1,Main            , 1
Up Type= 0
Dn Type= 3
Dn Slope=0.02596
DSS Import GetInterval= 0
DSS Import GetPeak= 0
DSS Import FillOption= 0

--- MIDFKRIVT1.g01 (geometry) ---

Geom Title=Geometry
Program Version=6.20

River Reach=MIDFKRIVT1      ,Main
Reach XY= 30
2236985.23200002706410.7380000052236372.84000003706376.692000002
2236111.28115006706628.4829495852235934.19100001706495.806999996
2235280.37100001706690.2520000192235056.84700003706872.543000013
2234737.47969991706847.0786254852234641.48200001706958.047000021
2234357.62800001706900.3209999952234240.45938641707114.763030355
2234019.54790039707137.0982749162234032.80200002707291.467000023
2233695.30200002707378.9669999932233330.51627493 707703.89942497
     2233451.552707913.3420000082233176.08378975708087.213564932
     2233219.521708201.188999996     2232999.729708449.799999997
     2232795.215709164.0359999982232770.59468669709684.763906404
     2232837.142709760.2169999932232740.35400002 709888.25500001
     2232801.552710149.5400000072232733.05109924710480.116644785
     2232842.785710601.7970000062232796.34299999710814.470000014
2232627.99283509710877.2744123792232641.19785699711084.008839145
2232371.70621113711298.1464505492232121.00875865 711898.70678398

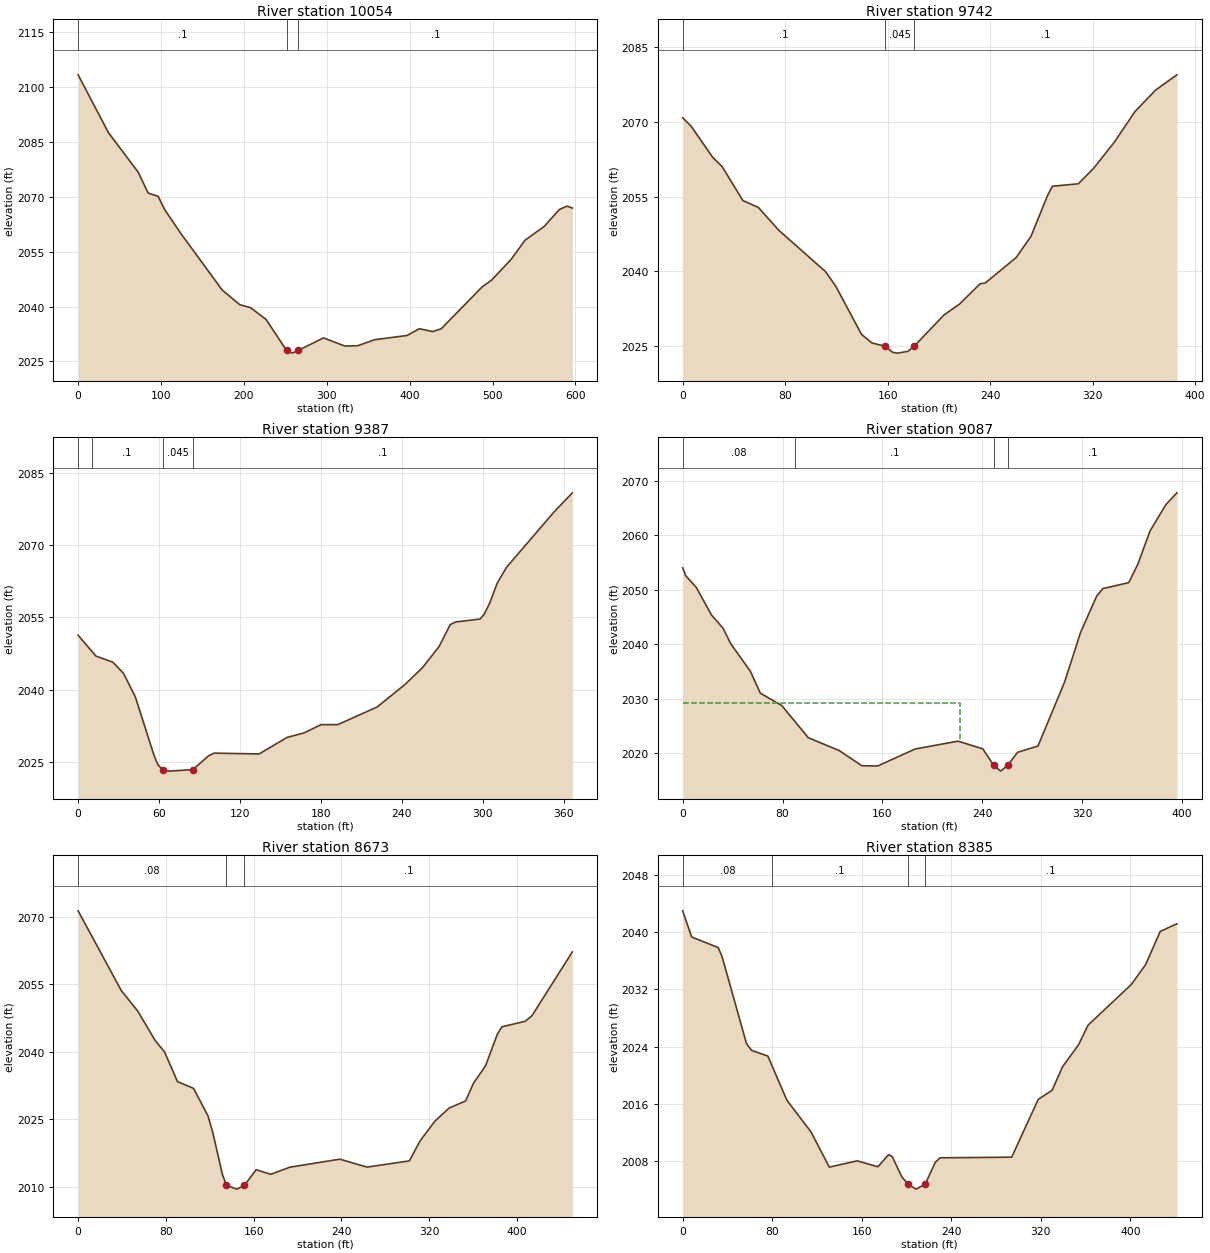
Type RM Length L Ch R = 1 ,10054   ,308.3,312.4,319
XS GIS Cut Line= 4
2236933.35181951706176.6865011462236930.60636408706350.151715665
2237059.16849128706508.1070596152237249.75441667706616.282474992
#Sta/Elev= 30
       0 2103.29    36.5 2087.53    72.5 2076.69    84.5 2070.99    96.5 2070.11
   104.5 2066.46   123.7 2060.03   173.9 2044.49     195 2040.52     208  2039.7
   226.7  2036.5  251.442028.027   258.3 2027.28  265.682028.027     296 2031.44
   321.8 2029.22   337.3  2029.3   357.9 2030.95   396.7 2032.09   411.7 2033.94
   427.9 2033.17   438.1 2033.93   487.2 2045.31     499 2047.25   522.4 2052.88
   539.3 2058.13   562.3 2061.87   580.7 2066.51   589.9 2067.43   596.3  2066.9
#Mann= 3 ,-1,0
       0      .1       0  251.44    .045       0  265.68      .1       0
Bank Sta=251.44,265.68
XS Rating Curve= 0 ,0
Exp/Cntr=0.3,0.1

Type RM Length L Ch R = 1 ,9742    ,360,355.4,351.4
XS GIS Cut Line= 2
2236727.44469126706258.5463304342236682.13982042706641.718034623
#Sta/Elev= 30
       0 2070.87     6.7 2069.13    23.3 2062.96    30.8 2061.05      47 2054.23
      59 2052.86    75.2 2048.21   111.4 2039.97   119.5 2037.01   139.6 2027.33
   147.7 2025.61  158.282024.923   163.8 2023.72   167.8 2023.56   175.8 2023.92
  180.612024.923     204 2031.24   216.1 2033.42   232.2  2037.5   236.3 2037.67
   260.4  2042.8   271.9 2047.04   284.6  2055.1   288.6 2057.11   308.8 2057.59
   320.9 2060.74     337 2065.98   353.1 2072.12   369.1 2076.42   385.8  2079.5
#Mann= 3 ,-1,0
       0      .1       0  158.28    .045       0  180.61      .1       0
Bank Sta=158.28,180.61
XS Rating Curve= 0 ,0
Exp/Cntr(USF)=0,0
Exp/Cntr=0.3,0.1

Type RM Length L Ch R = 1 ,9387    ,302.6,299.6,295.9
XS GIS Cut Line= 2
2236343.17432343706304.512196025 2236446.3978427706655.939233183
#Sta/Elev= 30
       0 2051.27    13.2 2046.96    25.7  2045.7    33.6  2043.4    42.4 2038.51
    56.1 2026.51    59.1 2024.45    62.6  2023.4    67.4 2023.11    85.1 2023.42
    96.6 2026.28   100.8 2026.84   134.1 2026.67   154.9  2030.1   167.5 2031.03
     180 2032.74   192.5 2032.75   221.7 2036.42   242.5 2041.13     255 2044.49
   267.5 2048.91   275.8 2053.49     280 2054.04   297.8 2054.63   300.9  2055.6
     305 2057.92   310.7 2062.12   317.5 2065.35   352.6 2076.79   366.3  2080.8
#Mann= 4 ,-1,0
       0     .08       0      10      .1       0    62.6    .045       0
    85.1      .1       0
Bank Sta=62.6,85.1
XS Rating Curve= 0 ,0
Exp/Cntr=0.3,0.1

Type RM Length L Ch R = 1 ,9087    ,411.1,414.2,409.2
XS GIS Cut Line= 2
 2236080.6159417706326.945040711 2236220.5032396706697.292890267
#Sta/Elev= 30
       0 2054.04     2.4 2052.58    10.9 2050.44    23.1 2045.36    32.3 2042.96
    38.6 2040.06    54.2 2035.05    62.2 2031.03    79.4 2028.75   100.6 2022.86
   125.5 2020.48   143.5 2017.71   156.3 2017.67   186.2 2020.78   220.5 2022.22
   240.4 2020.81  249.052017.813   254.7 2016.72  260.392017.797   268.3 2020.18
   284.6 2021.32     306 2033.12   318.8 2042.22   331.6 2048.82   336.6 2050.22
   357.3 2051.31   364.5 2054.63   374.4  2060.8   387.2 2065.67   395.9 2067.79
#Mann= 4 ,-1,0
       0     .08       0      90      .1       0  249.05    .045       0
  260.39      .1       0
#XS Ineff= 2 , 0
          222.09 2029.26
Permanent Ineff=
       F       F
Bank Sta=249.05,260.39
XS Rating Curve= 0 ,0
Exp/Cntr=0.3,0.1

Type RM Length L Ch R = 1 ,8673    ,285.6,287.9,286.8
XS GIS Cut Line= 2
2235807.78071538706377.5160990072235994.80371538706787.314099007
#Sta/Elev= 30
       0 2071.33    39.3 2053.63    54.4 2049.04      70 2042.59    78.8 2039.97
    90.6 2033.37   105.2 2031.88   118.3 2025.81   122.7 2022.13   131.5 2012.79
  135.13 2010.33   144.7 2009.49  151.582010.334   162.3 2013.81   175.5 2012.78
   193.1 2014.37   238.5 2016.14   263.4 2014.39   301.9 2015.76   311.8 2020.24
     325 2024.53   338.1 2027.49   353.3  2029.1   360.2 2032.93   371.4 2036.91
   382.2 2043.95   386.3 2045.56   407.6 2046.79   413.7 2048.02   450.5 2062.21
#Mann= 3 ,-1,0
       0     .08       0  135.13    .045       0  151.58      .1       0
Bank Sta=135.13,151.58
XS Rating Curve= 0 ,0
Exp/Cntr=0.3,0.1

Type RM Length L Ch R = 1 ,8385    ,528.3,531.1,528.4
XS GIS Cut Line= 3
2235616.46835829706438.728438925 2235572.2284063706522.995014147
2235693.36160818706847.421328753
#Sta/Elev= 30
       0 2042.96       8 2039.31    31.7 2037.84    35.1 2036.61      57 2024.44
    61.5  2023.5    76.1 2022.69    93.1 2016.53   114.6 2012.12     131  2007.2
   155.9 2008.08   174.4 2007.25   183.9 2008.94   187.2 2008.67   195.7 2005.86
  201.362004.829   208.5 2004.13  216.672004.828   225.6 2007.86   229.9  2008.5
   293.9 2008.59   317.6 2016.65     330 2017.92   339.3 2021.19   353.7 2024.29
   362.2 2027.02   400.7 2032.67   413.5 2035.44   426.6 2040.08   441.5 2041.15
#Mann= 4 ,-1,0
       0     .08       0      80      .1       0  201.36    .045       0
  216.67      .1       0
Bank Sta=201.36,216.67
XS Rating Curve= 0 ,0
Exp/Cntr(USF)=0,0
Exp/Cntr=0.3,0.1

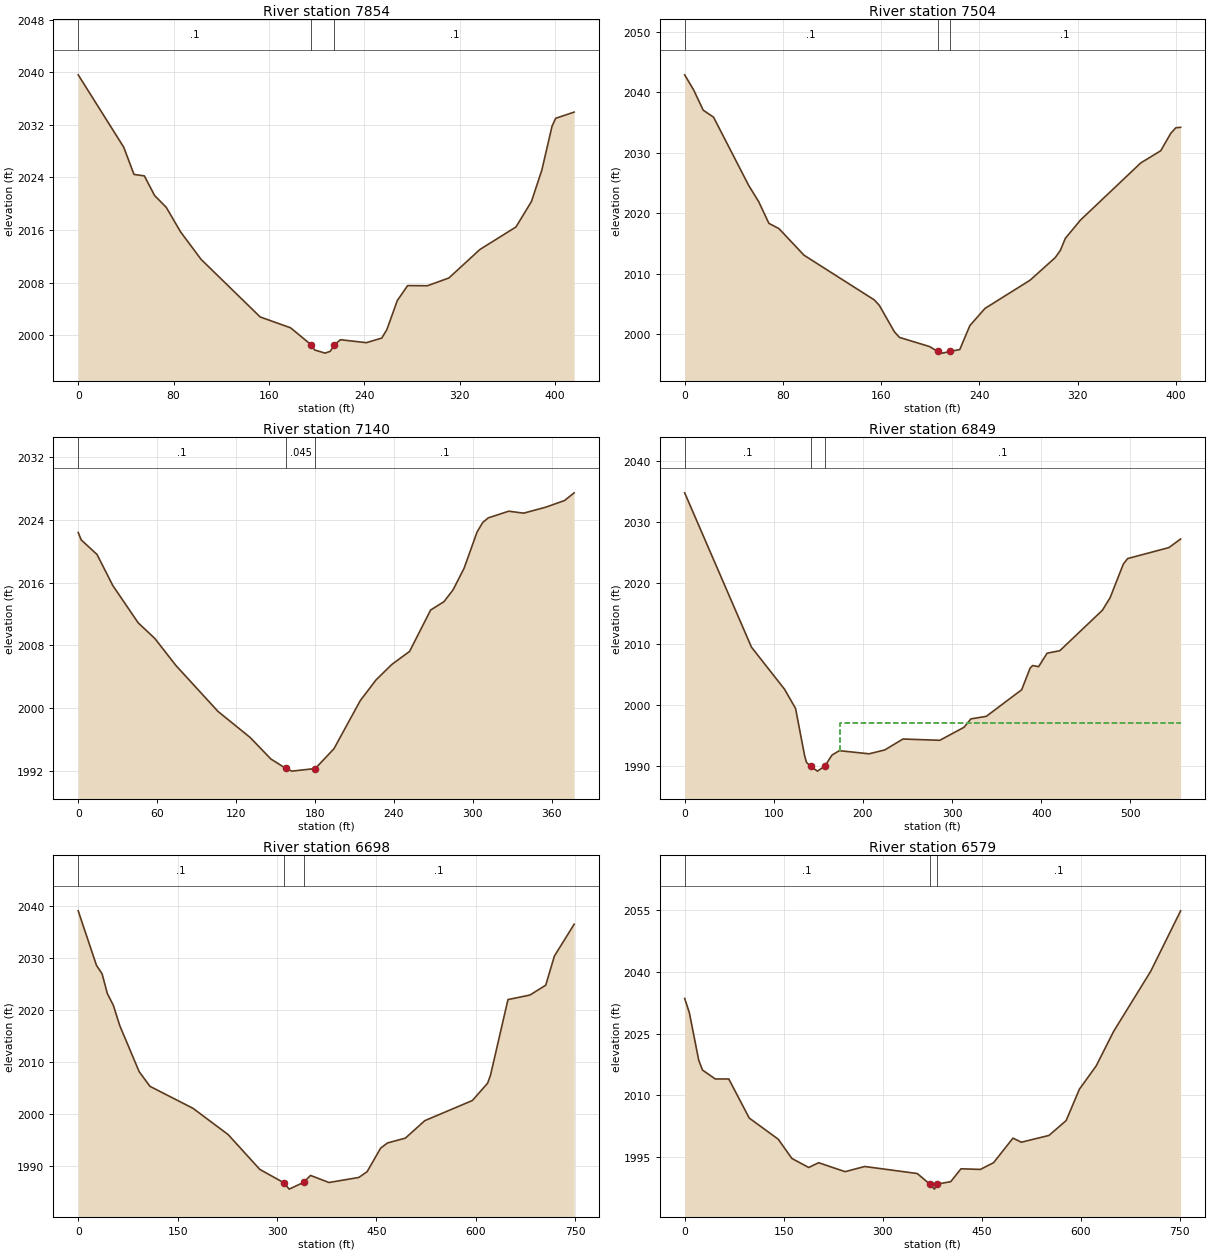
Type RM Length L Ch R = 1 ,7854    ,341.7,349.8,348
XS GIS Cut Line= 2
2235107.86503925706621.9363537392235267.38617978707006.290555969
#Sta/Elev= 30
       0  2039.6    38.2 2028.59    46.8 2024.45    55.5 2024.23    64.1 2021.24
    73.9 2019.44    85.8 2015.74   103.1 2011.53   152.7 2002.77   178.2 2001.12
  195.521998.525   198.4 1997.75   207.1 1997.27   211.4 1997.54  214.991998.525
     220 1999.31   241.7 1998.86   254.7 1999.56     259 2000.86   267.7 2005.26
   276.4 2007.54     293 2007.52     311  2008.7     337 2013.03   367.3 2016.46
   380.3 2020.34     389 2025.12   397.5 2031.75   400.6 2032.99   416.1 2033.93
#Mann= 3 ,-1,0
       0      .1       0  195.52    .045       0  214.99      .1       0
Bank Sta=195.52,214.99
XS Rating Curve= 0 ,0
Exp/Cntr=0.3,0.1

Type RM Length L Ch R = 1 ,7504    ,361.5,364.2,365.3
XS GIS Cut Line= 2
2234901.16580207706674.1789436282234986.98494377707069.006773013
#Sta/Elev= 30
       0 2042.92     7.2 2040.46    15.1 2037.07    23.5 2035.92    52.1 2024.64
    60.4  2021.9    68.6 2018.35    76.8 2017.48    97.2 2013.08   154.5 2005.68
   158.6 2004.77   170.9 2000.39     175 1999.48   199.6 1997.96  206.06 1997.16
   210.2 1996.88   215.9 1997.16   224.1 1997.47   232.3 2001.43   244.6 2004.27
   281.4 2008.95   301.9 2012.69     306 2013.87   310.1 2015.87   322.4 2018.89
   371.5 2028.34   387.8 2030.36     396 2033.25   400.1 2034.16     404 2034.24
#Mann= 3 ,-1,0
       0      .1       0  206.06    .045       0   215.9      .1       0
Bank Sta=206.06,215.9
XS Rating Curve= 0 ,0
Exp/Cntr=0.3,0.1

Type RM Length L Ch R = 1 ,7140    ,289.9,290.7,287.1
XS GIS Cut Line= 3
2234639.30588536706790.898453375 2234647.9573851707042.309666393
2234735.96076378707131.736711229
#Sta/Elev= 30
       0 2022.39     2.3 2021.44    14.3 2019.59    26.3 2015.63    45.6 2010.88
    58.3 2008.88    74.3 2005.44   106.3 1999.59   130.7 1996.28   146.5 1993.53
   157.8 1992.34   162.4 1991.99  180.22 1992.32   194.4 1994.84   214.4 2000.97
   226.4 2003.61   238.4 2005.58   251.9 2007.24   267.9 2012.51     278 2013.57
   284.9 2015.07   293.3 2017.82   303.2 2022.45   307.5 2023.66   311.7 2024.25
   327.3  2025.1   338.6 2024.85   355.6 2025.62   369.7 2026.46     377 2027.44
#Mann= 3 ,-1,0
       0      .1       0   157.8    .045       0  180.22      .1       0
Bank Sta=157.8,180.22
XS Rating Curve= 0 ,0
Exp/Cntr(USF)=0,0
Exp/Cntr=0.3,0.1

Type RM Length L Ch R = 1 ,6849    ,164.7,151.4,136
XS GIS Cut Line= 4
2234400.76999474706756.5793412422234373.24985799706864.013086848
2234388.60436557706935.132030476 2234702.2393125707136.310533317
#Sta/Elev= 30
       0  2034.8    74.9 2009.48   112.1 2002.55   124.4 1999.41   134.5 1991.69
   136.6 1990.57  141.211989.922   148.9 1989.13  157.061989.922   165.3 1991.77
   173.5 1992.49   206.9 1991.97   224.5 1992.61   244.9  1994.4   286.2 1994.19
   313.4 1996.33     321  1997.7   338.3 1998.12     378 2002.48   387.5 2006.04
   390.4 2006.46     397 2006.27   406.5 2008.48   420.8 2008.89   468.6 2015.54
   477.2 2017.58     492  2023.1   496.8 2024.01   543.1 2025.81   556.3 2027.22
#Mann= 3 ,-1,0
       0      .1       0  141.21    .045       0  157.06      .1       0
#XS Ineff= 2 , 0
                          173.74         1997.02
Permanent Ineff=
       F       F
Bank Sta=141.21,157.06
XS Rating Curve= 0 ,0
Exp/Cntr=0.3,0.1

Type RM Length L Ch R = 1 ,6698    ,117.3,118.7,120
XS GIS Cut Line= 6
2233969.35285706706937.1644887232234052.73106619707006.357889284
2234110.06442943706990.2928983522234254.61857424706988.673923675
2234535.75380576707054.9325072092234595.44262987707188.354584644
#Sta/Elev= 30
       0    2039    27.6 2028.54    36.1 2026.91    43.9 2023.16    53.1 2020.86
    62.7    2017      92 2008.16   108.3 2005.35   173.3 2001.13   226.2 1996.11
   274.2 1989.41   310.3 1986.87   318.4 1985.64  340.211986.933   350.6 1988.27
   378.5 1986.91   423.5 1987.88     436 1988.98   456.5 1993.51   466.8 1994.49
   493.8 1995.42   523.1 1998.77   594.9 2002.63   617.9 2005.95   622.3  2007.5
   648.6 2021.98   681.7 2022.85   705.6 2024.74   718.7 2030.33   748.5 2036.43
#Mann= 3 ,-1,0
       0      .1       0   310.3    .045       0  340.21      .1       0
Bank Sta=310.3,340.21
XS Rating Curve= 0 ,0
Exp/Cntr=0.3,0.1

Type RM Length L Ch R = 1 ,6579    ,242.4,249,240.8
XS GIS Cut Line= 6
2233896.56537334707034.7302871712233979.94358247707103.923687732
2234141.87775349707083.2198994972234345.00570561707115.400503572
2234462.96632204707152.4983056582234522.65514616707285.920383093
#Sta/Elev= 30
       0 2033.54     7.1 2030.06    21.3 2018.49      27 2016.11    46.3 2013.94
    66.8 2013.94    97.8 2004.42   141.8 1999.26   162.4 1994.58   187.9 1992.39
   202.9 1993.55     243 1991.37   272.7 1992.63   352.3 1990.92  371.221988.351
   378.3 1987.12  382.661988.352     403 1988.94   418.5 1992.07   447.9 1991.92
   467.9 1993.56   497.3 1999.54   509.9 1998.54   551.8 2000.19   577.8 2003.81
   597.9 2011.45   623.3 2017.11   649.6 2025.48     706 2040.18   751.2 2054.87
#Mann= 3 ,-1,0
       0      .1       0  371.22    .045       0  382.66      .1       0
Bank Sta=371.22,382.66
XS Rating Curve= 0 ,0
Exp/Cntr=0.3,0.1

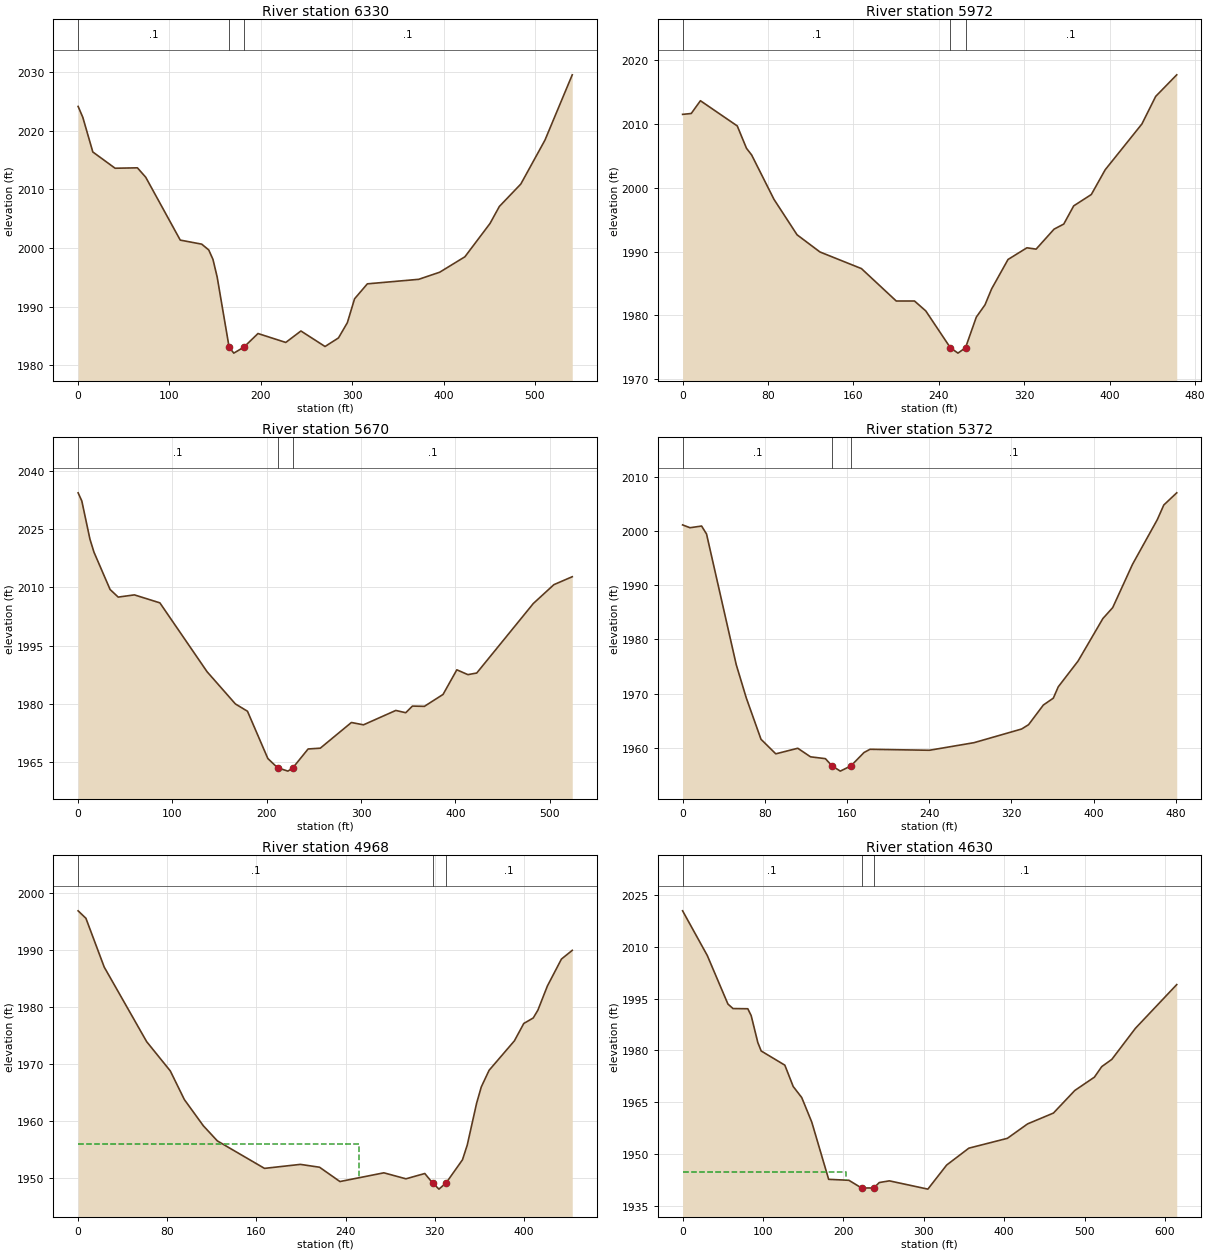
Type RM Length L Ch R = 1 ,6330    ,350.7,358.4,360.3
XS GIS Cut Line= 2
2233867.74299344 707061.223778352234338.45292263707327.677849199
#Sta/Elev= 30
       0 2024.11     5.1 2022.27    16.1 2016.35    40.5 2013.58    64.9 2013.65
      74 2012.05   111.8 2001.34   135.3 2000.65     143 1999.66   147.6 1998.06
   152.2 1995.06   165.31983.095   170.4 1982.09  181.331983.092   196.9 1985.43
   227.3 1983.91   243.9 1985.86   270.3 1983.22     285 1984.68   294.7 1987.27
   302.6 1991.34   316.6 1993.89   372.8 1994.66   395.8 1995.87   423.4  1998.5
   450.9 2004.18   461.1 2007.07   484.6 2010.89     511 2018.36   540.9 2029.49
#Mann= 3 ,-1,0
       0      .1       0   165.3    .045       0  181.33      .1       0
Bank Sta=165.3,181.33
XS Rating Curve= 0 ,0
Exp/Cntr(USF)=0,0
Exp/Cntr=0.3,0.1

Type RM Length L Ch R = 1 ,5972    ,300.4,302.1,300.5
XS GIS Cut Line= 2
2233775.59713756707137.6722524612233947.29028458707567.431786093
#Sta/Elev= 30
       0 2011.51     8.1 2011.65    16.7 2013.65    51.2  2009.7    59.8 2006.21
    64.7 2005.14    85.6 1998.19   107.2 1992.64   128.7 1989.94   167.5 1987.34
   200.1 1982.26   217.2 1982.26   227.8  1980.7  250.781974.936   257.9 1974.09
  264.971974.934   275.1 1979.74   283.2 1981.65   289.4 1984.15   304.8 1988.77
   322.5  1990.6   331.1 1990.39   347.9 1993.52     357 1994.32   366.3 1997.17
   382.8 1998.95   395.8 2002.83   430.2 2010.01   443.1 2014.33   462.8 2017.71
#Mann= 3 ,-1,0
       0      .1       0  250.78    .045       0  264.97      .1       0
Bank Sta=250.78,264.97
XS Rating Curve= 0 ,0
Exp/Cntr(USF)=0,0
Exp/Cntr=0.3,0.1

Type RM Length L Ch R = 1 ,5670    ,301.4,297.9,290.8
XS GIS Cut Line= 3
2233535.80603376 707245.502836862233639.44029766707515.010303886
2233799.46306186707687.454937974
#Sta/Elev= 30
       0 2034.32     3.9 2032.24    12.5 2022.44    16.8 2019.06    33.9 2009.46
    42.5  2007.5    59.7 2008.07    86.7 2006.02   136.8 1988.29   166.8 1980.02
   179.6 1978.14   201.2 1965.98  211.521963.606   222.5 1962.74  227.751963.608
   243.9 1968.44   256.8 1968.64   289.8 1975.25   302.6 1974.65   336.9 1978.35
   347.4 1977.76   354.5 1979.47   367.2  1979.4     387 1982.47   401.6  1988.8
   413.3 1987.56   422.7 1987.97   482.7 2005.85   504.5  2010.7     524 2012.74
#Mann= 3 ,-1,0
       0      .1       0  211.52    .045       0  227.75      .1       0
Bank Sta=211.52,227.75
XS Rating Curve= 0 ,0
Exp/Cntr=0.3,0.1

Type RM Length L Ch R = 1 ,5372    ,404.1,403.2,395.1
XS GIS Cut Line= 2
2233272.85262349707554.5773818442233671.83569649707823.023353739
#Sta/Elev= 30
       0 2001.12     7.2  2000.6    18.5 2000.91    23.3 1999.44    52.2 1975.33
      62 1969.18    76.3 1961.56    90.7 1958.87   112.1  1959.9   124.5 1958.32
     139 1957.98  145.391956.655   153.5 1955.68  163.861956.655   176.6 1959.12
   182.4 1959.71   240.2 1959.53   283.6 1960.93   329.9 1963.45   336.7 1964.25
   351.1 1967.88   360.8 1969.15   365.6 1971.24   384.9    1976     409 1983.83
   418.6 1985.86   437.9 1993.86     462 2002.09   468.3 2004.79   480.9 2007.04
#Mann= 3 ,-1,0
       0      .1       0  145.39    .045       0  163.86      .1       0
Bank Sta=145.39,163.86
XS Rating Curve= 0 ,0
Exp/Cntr=0.3,0.1

Type RM Length L Ch R = 1 ,4968    ,338.4,338.8,336.9
XS GIS Cut Line= 2
2233145.99361218707802.9201460182233565.31692131707946.746460888
#Sta/Elev= 30
       0 1996.86       7 1995.55    23.4    1987    61.5 1973.91    82.7 1968.78
    95.3 1963.76   112.3 1959.17   124.9 1956.51   167.2 1951.69   199.4 1952.39
   216.6 1951.89   234.9 1949.38   274.3 1950.91   294.1 1949.86     311 1950.79
  317.961949.151   323.7 1948.05  330.18 1949.15   344.8 1953.19   349.1 1955.78
   357.5 1963.12   361.7 1965.98   368.7 1968.89   391.4 1974.06   399.8  1977.1
   408.3 1978.07   412.5 1979.45     421 1983.68   433.6  1988.4   443.3 1989.93
#Mann= 3 ,-1,0
       0      .1       0  317.96    .045       0  330.18      .1       0
#XS Ineff= 2 , 0
          251.89    1956
Permanent Ineff=
       F       F
Bank Sta=317.96,330.18
XS Rating Curve= 0 ,0
Exp/Cntr=0.3,0.1

Type RM Length L Ch R = 1 ,4630    ,331.1,332.9,329.5
XS GIS Cut Line= 2
2232954.86983744708019.7905529132233541.13029569708204.669224998
#Sta/Elev= 30
       0 2020.44    30.7  2007.5    56.4 1993.42    62.7 1992.12    81.1 1992.06
    85.3 1990.09    93.6 1982.25    97.8 1979.82   127.2 1975.71   137.6 1969.53
   148.2 1966.33   160.7 1959.21   181.7 1942.63   206.9 1942.35   222.61940.122
  237.74 1940.12   244.7  1941.7   257.2 1942.19   305.1 1939.79   328.5 1946.77
   356.1 1951.66     404 1954.51   429.2  1958.7   461.3 1961.83   487.9 1968.38
   512.3 1972.24   521.4 1975.29     534  1977.4   563.3 1986.39   614.7 1999.06
#Mann= 3 ,-1,0
       0      .1       0   222.6    .045       0  237.74      .1       0
#XS Ineff= 2 , 0
          203.58 1944.78
Permanent Ineff=
       F       F
Bank Sta=222.6,237.74
XS Rating Curve= 0 ,0
Exp/Cntr=0.3,0.1

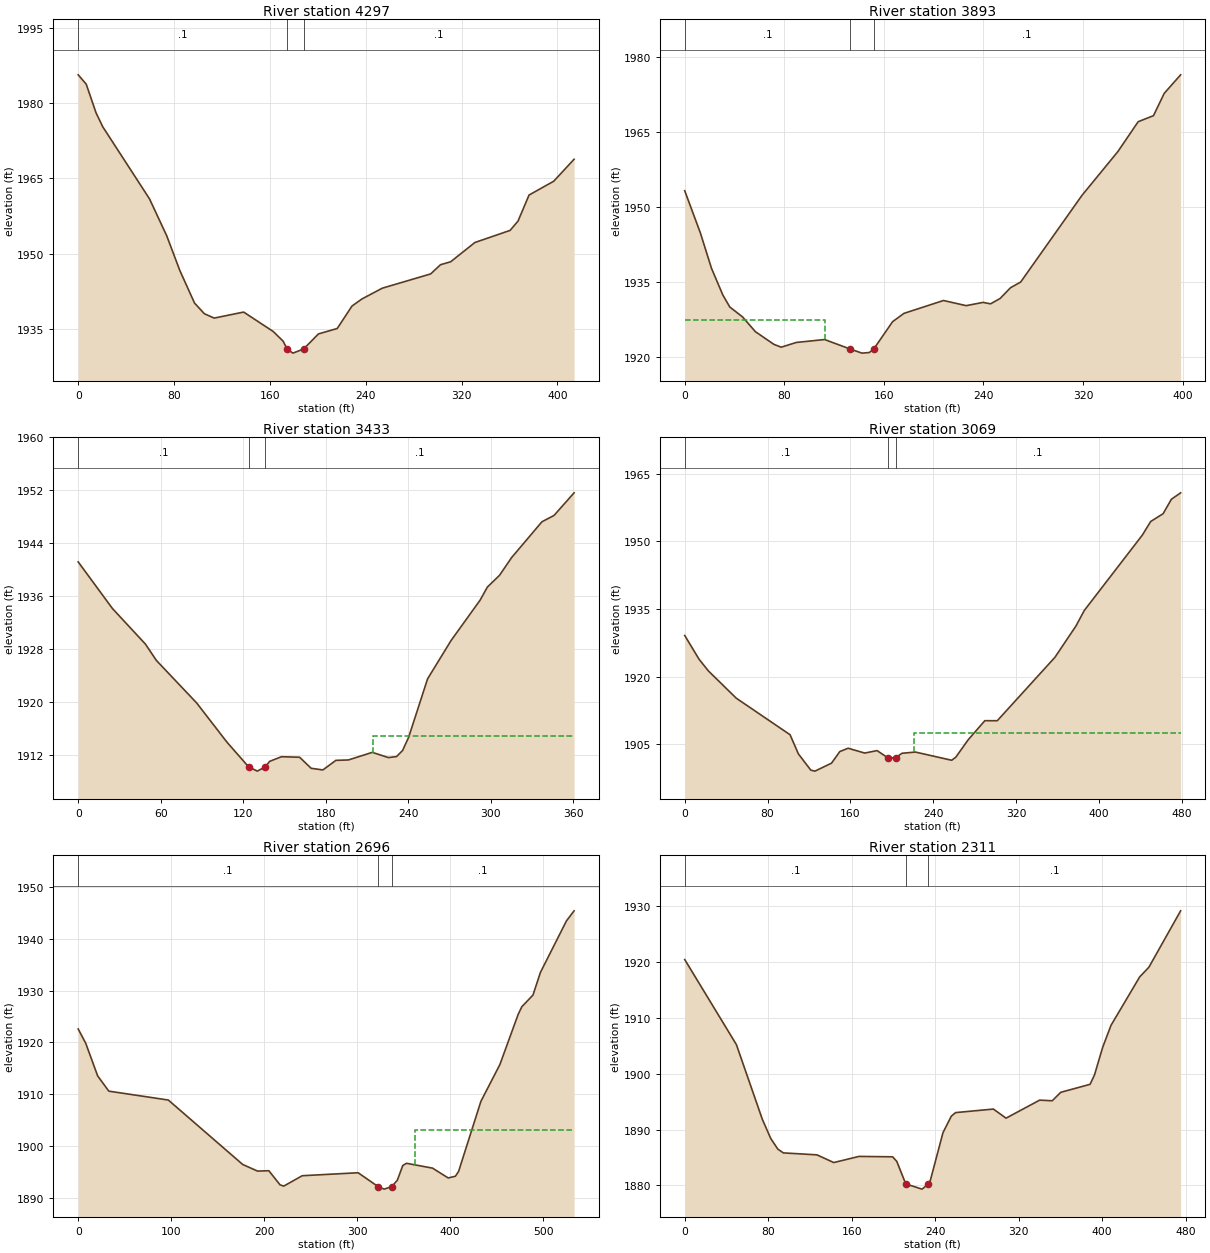
Type RM Length L Ch R = 1 ,4297    ,400.1,403.3,404.6
XS GIS Cut Line= 2
2232921.61391614708291.0850714622233324.74105069708384.714599486
#Sta/Elev= 30
       0 1985.62     6.7 1983.76    14.9 1978.05    20.5 1975.28    59.5 1960.95
    73.9 1953.59    84.8  1946.7    97.1 1940.21   105.3 1938.09   113.5 1937.22
   138.1 1938.42   162.8 1934.55     171 1932.64  174.371931.065   179.2 1930.25
  188.121931.067   200.5 1934.07   216.2 1935.15   228.5 1939.61   236.7 1941.01
   253.8 1943.17   294.2 1946.01   302.4 1947.84   310.9 1948.43   331.1 1952.26
   360.5 1954.67   367.1 1956.52   376.3  1961.7   396.9 1964.45   413.9 1968.83
#Mann= 3 ,-1,0
       0      .1       0  174.37    .045       0  188.12      .1       0
Bank Sta=174.37,188.12
XS Rating Curve= 0 ,0
Exp/Cntr(USF)=0,0
Exp/Cntr=0.3,0.1

Type RM Length L Ch R = 1 ,3893    ,457.3,460.9,458.5
XS GIS Cut Line= 3
2232829.28479823708619.058488508 2233052.9553374708739.996628872
2233193.39962943708772.506881659
#Sta/Elev= 30
       0 1953.26    12.6 1944.79    21.5 1937.73    30.6 1932.39    36.2 1929.98
    46.5 1927.98    56.8 1925.03    71.7 1922.49    77.5 1921.93    89.7 1922.88
   112.4 1923.46   132.81921.573   142.4 1920.74   148.3 1920.86  151.881921.572
     167 1927.04   176.1  1928.7   207.9 1931.28   226.1 1930.25   239.7  1930.9
   245.7 1930.61   253.4 1931.69   261.7 1933.83   269.9 1934.98   319.2 1952.35
     348 1961.11   364.3 1967.09   376.6  1968.3   385.2 1972.76   398.4 1976.48
#Mann= 3 ,-1,0
       0      .1       0   132.8    .045       0  151.88      .1       0
#XS Ineff= 2 , 0
          112.66 1927.36
Permanent Ineff=
       F       F
Bank Sta=132.8,151.88
XS Rating Curve= 0 ,0
Exp/Cntr(USF)=0,0
Exp/Cntr=0.3,0.1

Type RM Length L Ch R = 1 ,3433    ,366.3,363.8,361.5
XS GIS Cut Line= 3
2232699.24378708709067.6999769582232772.06675332 709069.00038707
2233033.44918572709189.938527435
#Sta/Elev= 30
       0 1941.18    24.9 1934.13    48.9 1928.75    56.9 1926.27    86.2 1919.84
   108.2 1913.92  123.961910.181   130.3 1909.53  135.951910.152   139.3 1911.01
   147.9 1911.71   161.1 1911.63   169.5 1909.96     178 1909.71   187.5 1911.16
   196.6 1911.22     214 1912.37   225.7 1911.58   231.6 1911.73     236 1912.65
   240.4 1914.64   254.2 1923.49   271.3 1929.29   292.4 1935.39   297.7 1937.37
   306.5 1939.14   315.4 1941.85   337.4 1947.25   346.2 1948.21   360.8 1951.63
#Mann= 3 ,-1,0
       0      .1       0  123.96    .045       0  135.95      .1       0
#XS Ineff= 2 , 0
                          214.58         1914.91
Permanent Ineff=
       F       F
Bank Sta=123.96,135.95
XS Rating Curve= 0 ,0
Exp/Cntr(USF)=0,0
Exp/Cntr=0.3,0.1

Type RM Length L Ch R = 1 ,3069    ,371.1,372.6,371.2
XS GIS Cut Line= 3
2232575.70482649709411.8992320642232653.72943318709450.911535408
2233045.15287673709443.109074739
#Sta/Elev= 30
       0 1929.11    13.9 1923.82    22.9 1921.24    49.7 1915.21   101.7 1907.09
   109.7 1902.85   121.7 1899.24   125.7 1899.02   141.7 1900.79   149.7 1903.36
   157.7  1904.1   173.7 1903.03   185.7 1903.57  195.971901.993   203.51901.981
   209.7 1902.98   222.7 1903.25   257.7 1901.43   261.7 1902.12   273.7    1906
   289.7 1910.21   301.7  1910.2   357.4 1924.28   377.7 1931.23   385.7 1934.66
   441.8  1951.4   449.8  1954.4   461.8 1956.13   469.8 1959.34   478.7 1960.76
#Mann= 3 ,-1,0
       0      .1       0  195.97    .045       0   203.5      .1       0
#XS Ineff= 2 , 0
                          221.14         1907.48
Permanent Ineff=
       F       F
Bank Sta=195.97,203.5
XS Rating Curve= 0 ,0
Exp/Cntr(USF)=0,0
Exp/Cntr=0.3,0.1

Type RM Length L Ch R = 1 ,2696    ,384.5,384.8,381.3
XS GIS Cut Line= 2
2232507.26797816709774.1879782852233040.31843891709763.170722839
#Sta/Elev= 30
       0  1922.6     8.1 1919.85    20.9 1913.58    32.9 1910.64    96.9 1908.93
   176.9 1896.53   192.9 1895.26     205 1895.33     217 1892.62     221 1892.37
   240.9 1894.37     301 1894.94  322.61 1892.26     329 1891.79     337 1892.27
   343.1 1893.48     349 1896.33     353 1896.76     381 1895.83   397.8 1893.94
   405.6 1894.27     409 1895.19     433 1908.68   453.4 1915.75     473 1925.38
     477 1926.88     489 1929.13     497 1933.48     525  1943.4   533.2 1945.33
#Mann= 3 ,-1,0
       0      .1       0  322.61    .045       0     337      .1       0
#XS Ineff= 2 , 0
                          362.38         1903.25
Permanent Ineff=
       F       F
Bank Sta=322.61,337
XS Rating Curve= 0 ,0
Exp/Cntr(USF)=0,0
Exp/Cntr=0.3,0.1

Type RM Length L Ch R = 1 ,2311    ,309.1,313.3,320
XS GIS Cut Line= 2
2232574.28402647710118.0797596022233046.38751415710064.043818241
#Sta/Elev= 30
       0 1920.45    49.5 1905.22    74.4 1891.82    82.4 1888.41    89.2  1886.5
    94.5 1885.82   126.7 1885.47   142.8 1884.09     167 1885.19   199.2 1885.12
   203.2  1884.3  211.821880.261   227.4 1879.33  233.591880.262   235.4 1880.93
   247.5 1889.46   255.5 1892.41   259.6 1893.04   295.8 1893.67   307.9 1892.04
   340.1 1895.27   352.2 1895.16   360.3 1896.67   388.4  1898.1   392.7  1899.8
   400.5 1904.73   408.5 1908.67     436 1917.35   444.8 1919.08   475.2 1929.18
#Mann= 3 ,-1,0
       0      .1       0  211.82    .045       0  233.59      .1       0
Bank Sta=211.82,233.59
XS Rating Curve= 0 ,0
Exp/Cntr(USF)=0,0
Exp/Cntr=0.3,0.1

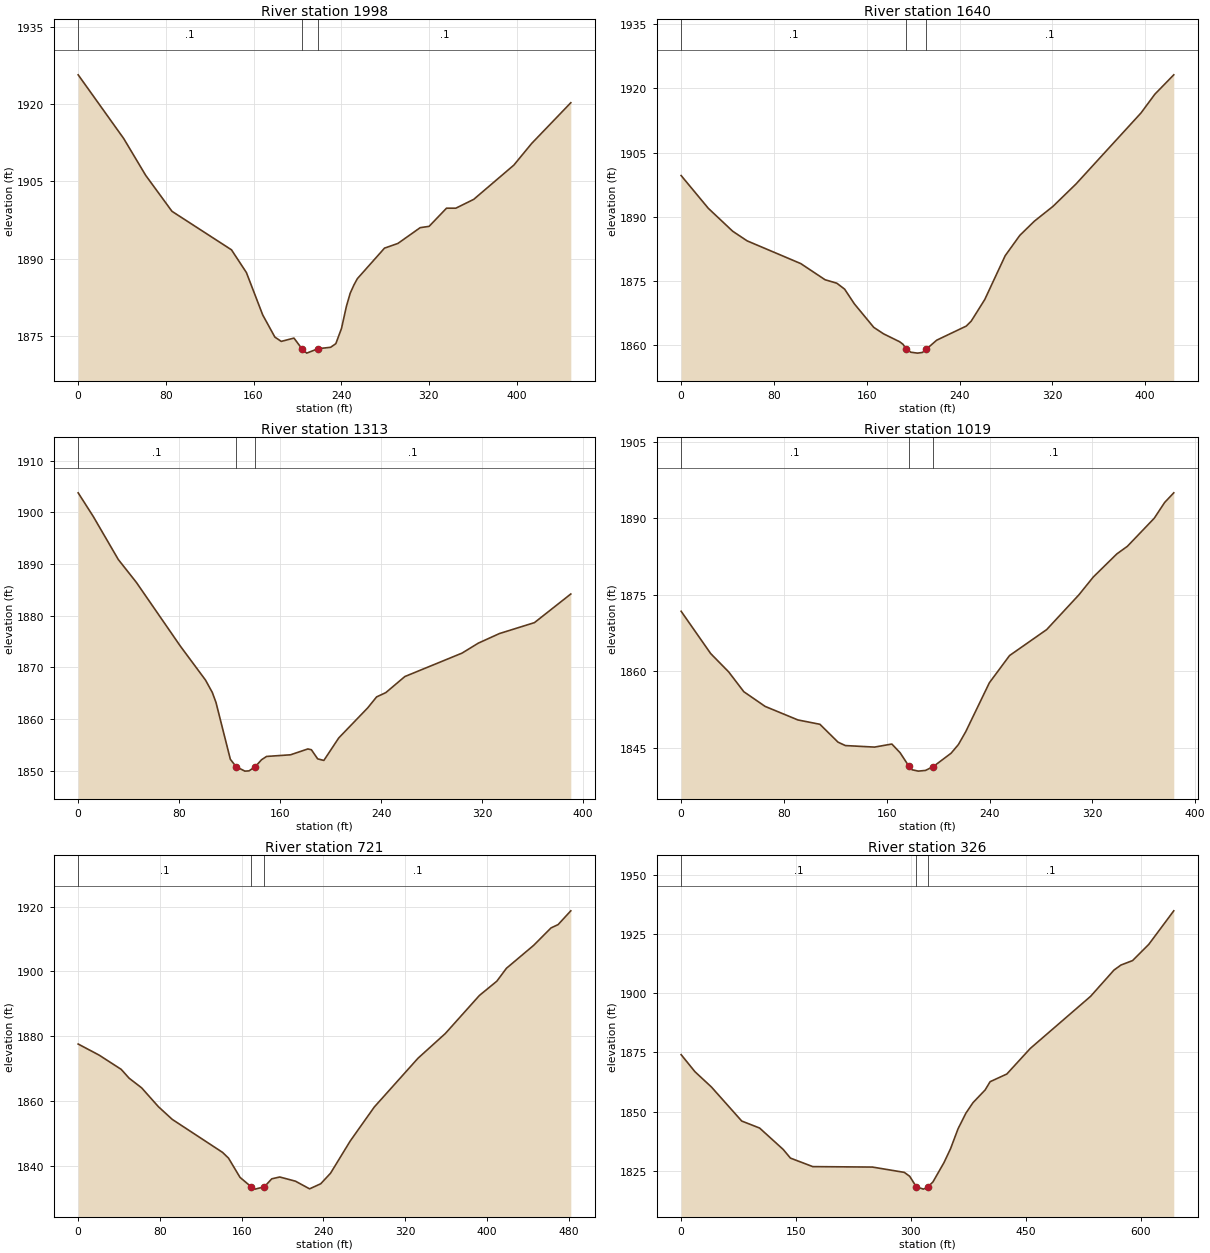
Type RM Length L Ch R = 1 ,1998    ,355.1,358.5,352.2
XS GIS Cut Line= 4
 2232586.6080131710354.1315034432232712.69187627710358.871498299
2232825.50375385710431.8674190852233011.31155222 710465.99538205
#Sta/Elev= 30
       0 1925.71    41.6 1913.32    61.6 1906.19    85.6  1899.2   139.9 1891.72
   153.5 1887.31   168.4 1879.07   179.5 1874.77   185.3 1873.94   196.9 1874.58
   204.1 1872.53   208.5 1871.66   218.8 1872.51   230.4  1872.8   235.1  1873.5
   240.3 1876.48   244.7 1880.71   248.2 1883.29   251.6 1884.89   254.7 1886.11
   279.5 1892.05   291.7 1892.96   312.1 1896.03   320.2 1896.28   336.1 1899.81
   344.6 1899.81   360.9 1901.52   397.5 1908.17   413.7 1912.36   449.5 1920.29
#Mann= 3 ,-1,0
       0      .1       0   204.1    .045       0   218.8      .1       0
Bank Sta=204.1,218.8
XS Rating Curve= 0 ,0
Exp/Cntr(USF)=0,0
Exp/Cntr=0.3,0.1

Type RM Length L Ch R = 1 ,1640    ,320.8,326.8,326.8
XS GIS Cut Line= 3
2232617.89197915710630.9472030472232905.13566744710721.955104287
 2233028.3755337710725.747100172
#Sta/Elev= 30
       0 1899.65    23.4    1892    44.4 1886.64    56.9 1884.38   103.1 1879.07
   124.1 1875.29   134.2 1874.48   140.9  1873.1   149.3 1869.66     166 1864.17
   174.4 1862.66   188.4 1860.79   191.2 1860.21  194.21 1859.05     198 1858.35
   203.8 1858.14     208  1858.3  211.261859.052   220.3 1861.17   245.8 1864.47
     250 1865.61   261.7 1870.67   279.3 1880.91   291.9 1885.66   304.4 1888.97
   320.4 1892.42   340.4 1897.69   396.4 1914.29   408.3 1918.66   424.6 1923.19
#Mann= 3 ,-1,0
       0      .1       0  194.21    .045       0  211.26      .1       0
Bank Sta=194.21,211.26
XS Rating Curve= 0 ,0
Exp/Cntr(USF)=0,0
Exp/Cntr=0.3,0.1

Type RM Length L Ch R = 1 ,1313    ,290.1,293.8,293.3
XS GIS Cut Line= 3
2232534.49145602710786.4145630982232758.21921323710948.522387182
2232864.39509801710990.234341917
#Sta/Elev= 30
       0 1903.77      12 1899.18    31.8 1890.87    46.1 1886.45    81.1 1874.07
   100.9 1867.55   106.3 1865.15   109.2 1863.23   120.6 1852.22  125.171850.793
   132.1 1849.93   135.4 1849.98  140.371850.794   145.3 1852.13   149.3 1852.77
   168.3 1853.09     182 1854.22   184.8 1854.07   189.8  1852.3   194.7    1852
   206.5 1856.35   229.5 1862.18   236.5 1864.29   243.8 1865.12   258.9 1868.23
   304.2 1872.76   317.1 1874.69   333.8 1876.54   361.6 1878.66   390.4  1884.2
#Mann= 3 ,-1,0
       0      .1       0  125.17    .045       0  140.37      .1       0
Bank Sta=125.17,140.37
XS Rating Curve= 0 ,0
Exp/Cntr(USF)=0,0
Exp/Cntr=0.3,0.1

Type RM Length L Ch R = 1 ,1019    ,296.7,298,297.1
XS GIS Cut Line= 2
2232454.85954243711006.3503244282232747.79122455711253.778055923
#Sta/Elev= 30
       0 1871.75      23 1863.46      37 1859.87    48.8 1855.98    65.4  1853.1
    90.9 1850.45     108  1849.6   122.1  1846.1   127.8 1845.43   150.5 1845.13
     164 1845.73   170.4 1844.03  177.421841.327   179.7 1840.69   184.6 1840.42
   190.2 1840.56  196.331841.326   210.1 1843.93   215.8 1845.63   221.5 1848.15
   239.9 1857.74   255.6 1863.07   284.5 1868.16   309.5 1874.95   320.8 1878.47
   339.1 1882.99   347.3 1884.48   368.2 1889.98   376.3 1893.07   383.4 1894.96
#Mann= 3 ,-1,0
       0      .1       0  177.42    .045       0  196.33      .1       0
Bank Sta=177.42,196.33
XS Rating Curve= 0 ,0
Exp/Cntr(USF)=0,0
Exp/Cntr=0.3,0.1

Type RM Length L Ch R = 1 ,721     ,392.5,394.7,392.5
XS GIS Cut Line= 2
2232238.59583906711184.8538488432232623.64727306711475.105385719
#Sta/Elev= 30
       0  1877.6    20.5 1874.18    42.1 1869.79    49.9 1867.05    62.1 1864.09
    78.5 1858.28    92.1 1854.35   141.3 1844.18   147.2 1842.39   158.4 1836.47
  169.411833.549   173.3 1832.84   182.3 1833.58   189.5 1836.02   197.3 1836.58
   212.7 1835.29   226.5 1832.93   237.4 1834.49     247 1837.74   266.3 1847.69
   289.8 1858.15   332.6 1873.21   359.4 1880.85   392.7 1892.57   409.8 1896.99
   419.2 1900.97   445.8 1908.03   462.8 1913.41   469.8 1914.45   482.2 1918.69
#Mann= 3 ,-1,0
       0      .1       0  169.41    .045       0   182.3      .1       0
Bank Sta=169.41,182.3
XS Rating Curve= 0 ,0
Exp/Cntr(USF)=0,0
Exp/Cntr=0.3,0.1

Type RM Length L Ch R = 1 ,326     ,211.2,211.9,214.1
XS GIS Cut Line= 4
2232007.66515055 711396.471997242232078.92878462711501.142551983
2232292.16478754711648.7356626492232527.53901772711752.768471565
#Sta/Elev= 30
       0 1874.08    18.1 1866.86    39.6 1860.41    79.1 1846.07   102.5  1843.1
   133.3 1834.07   142.7 1830.43   171.9 1826.83   249.8 1826.64   291.4  1824.4
   298.4 1822.77  307.191818.275   316.5 1817.33  322.231818.273   328.8 1820.36
   343.2  1828.5   351.8 1834.37   361.6 1842.79   371.9 1849.41   381.1 1853.81
     397 1859.19   403.5 1862.67   425.3  1865.9   455.9 1876.69   534.7 1898.69
   565.2 1909.76   574.3 1911.89   589.5 1913.77   610.7 1920.63   643.3 1934.77
#Mann= 3 ,-1,0
       0      .1       0  307.19    .045       0  322.23      .1       0
Bank Sta=307.19,322.23
XS Rating Curve= 0 ,0
Exp/Cntr(USF)=0,0
Exp/Cntr=0.3,0.1

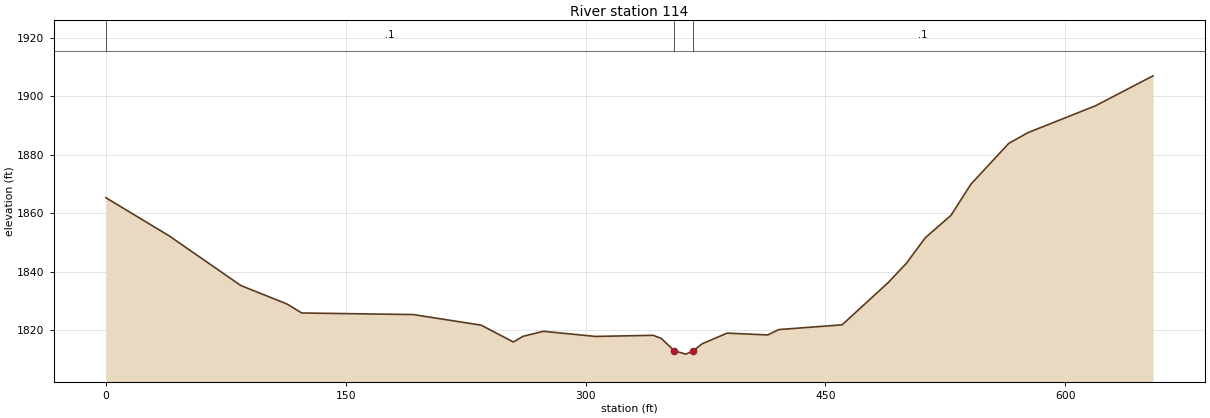
Type RM Length L Ch R = 1 ,114     ,,,
XS GIS Cut Line= 4
2231931.09835008711498.9922500492232018.52492187711650.672085449
2232178.03703988711849.8450574992232402.23049685711865.463028659
#Sta/Elev= 30
       0 1865.31    39.5 1852.29    84.4 1835.28   113.3 1828.96   122.5 1825.89
   192.3 1825.35   234.7 1821.73   254.9 1815.96   260.9 1817.91   273.7 1819.63
   306.1 1817.87   342.3 1818.26   347.4 1817.19  355.551812.943   362.8 1811.82
  367.381812.942     373 1815.37   388.6 1819.01     414 1818.38   420.9 1820.22
   460.5 1821.84   489.3 1836.27   500.6 1842.81   512.6 1851.65   528.6 1859.28
     541 1869.88   564.7 1883.87   576.7 1887.55   619.1 1896.77     655 1906.99
#Mann= 3 ,-1,0
       0      .1       0  355.55    .045       0  367.38      .1       0
Bank Sta=355.55,367.38
XS Rating Curve= 0 ,0
Exp/Cntr(USF)=0,0
Exp/Cntr=0.3,0.1
LCMann Table=0

Chan Stop Cuts=-1
Use User Specified Reach Order=0
Composite Channel Slope=5